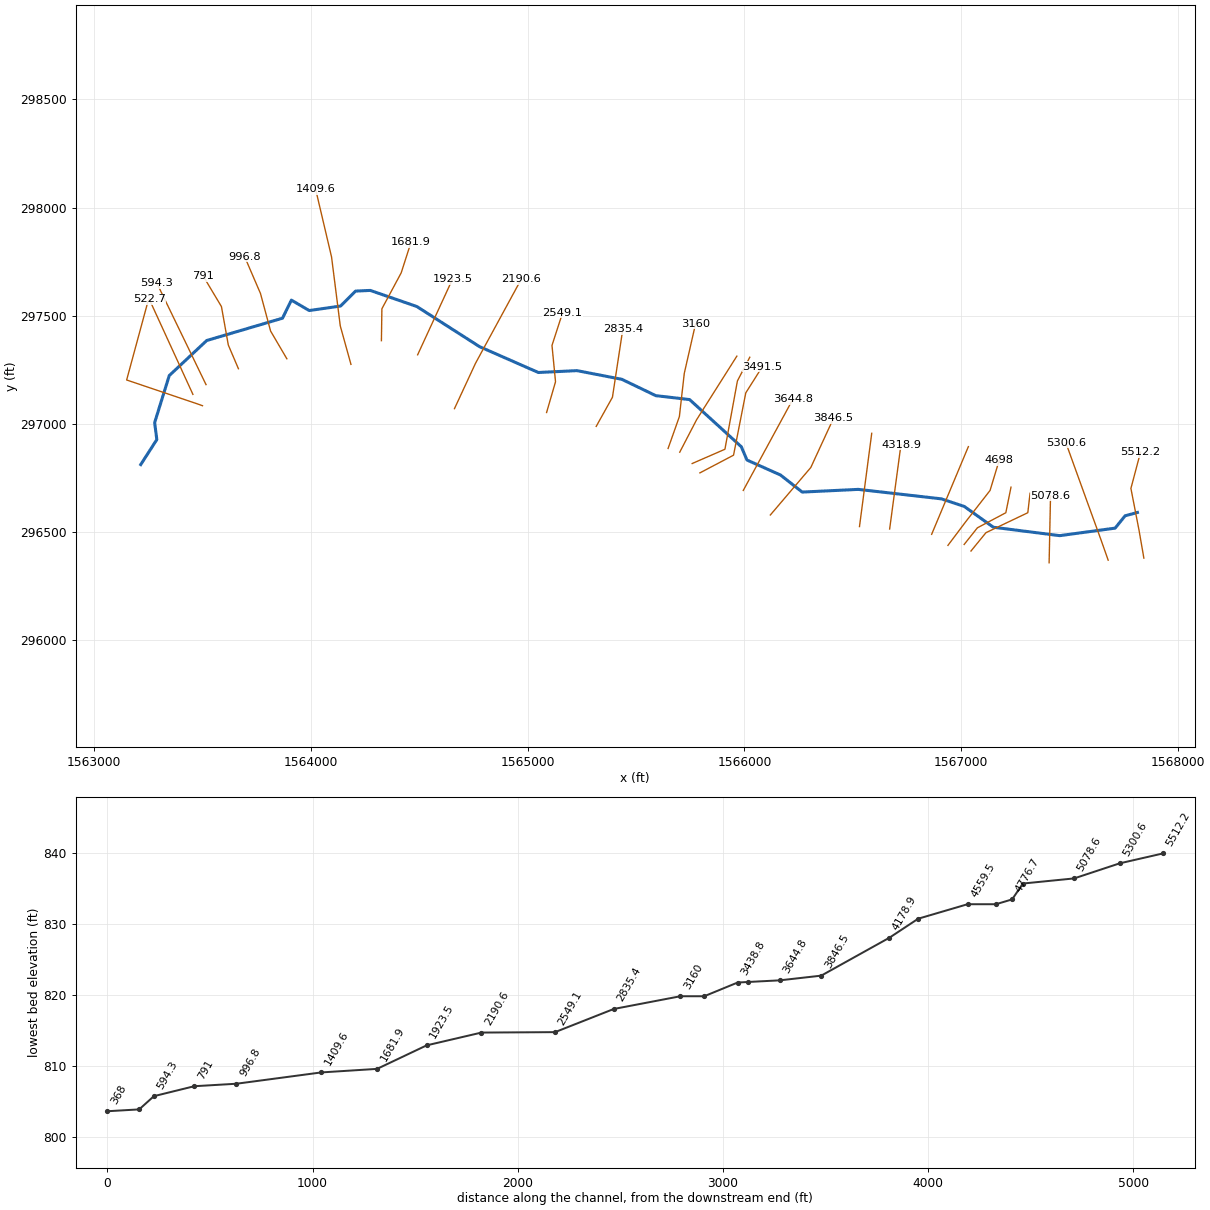
--- BCKRN.prj (project) ---

Proj Title=BCKRN
Current Plan=p01
Default Exp/Contr=0,0
English Units
Geom File=g01
Flow File=f01
Plan File=p01
BEGIN DESCRIPTION:
END DESCRIPTION:
DSS Export Rating Curves= 0
DSS Export Rating Curve Sorted= 0
DSS Export Volume Flow Curves= 0
DXF OffsetX= 0
DXF OffsetY= 0
DXF ScaleX= 0
DXF ScaleY= 0

--- BCKRN.p01 (plan) ---

Plan Title=Floodplain
Program Version=4.00
Geom File=g01
Flow File=f01
K Sum by GR=0
Std Step Tol=0.01
Critical Tol=0.01
Num of Std Step Trials=20
Max Error Tol=0.3
Flow Tol Ratio=0.001
Split Flow NTrial=30
Split Flow Tol=0.02
Split Flow Ratio=0.02
Log Output Level=0
Friction Slope Method=1
Unsteady Friction Slope Method=2
Unsteady Bridges Friction Slope Method=1
Global Log Level=0
CheckData=False
Run HTab=0
Run UNet=0
Run PostProcess=0
UNET Theta=0
UNET Theta Warmup=0
UNET ZTol=0
UNET ZSATol=0
UNET MxIter=0
UNET MaxInSteps=0
UNET DtIC=0
UNET DtMin=0
UNET MaxCRTS=0
UNET WFStab=0
UNET SFStab=0
UNET WFX=0
UNET SFX=0
UNET DSS MLevel=0
UNET DZMax Abort=0
UNET Convert EG Bridges=0
UNET Use Existing IB Tables=0
UNET Froude Limit=0
UNET Froude Power=0
Write IC File=0
Echo Input=False
Echo Output=False
Write Detailed=0

--- BCKRN.f01 (steady flow) ---

Flow Title=NFF Regression Equation
Program Version=4.10
Number of Profiles= 1
Profile Names=P100yr
River Rch & RM=BCKRN,Main            ,5512.2
878.4071
River Rch & RM=BCKRN,Main            ,5300.6
 929.017
River Rch & RM=BCKRN,Main            ,4776.7
1012.561
River Rch & RM=BCKRN,Main            ,791
1113.204
River Rch & RM=BCKRN,Main            ,594.3
1116.928
Boundary for River Rch & Prof#=BCKRN,Main            , 1
Up Type= 0
Dn Type= 3
Dn Slope=0.005
DSS Import GetInterval= 0
DSS Import GetPeak= 0
DSS Import FillOption= 0

--- BCKRN.g01 (geometry) ---

Geom Title=USGS 10m DEM
Program Version=4.10

River Reach=BCKRN           ,Main
Reach XY= 30
     1567812.372      296590.204     1567755.362      296574.705
     1567709.529      296517.761     1567453.973      296483.039
     1567147.723      296521.928     1567013.761      296617.931
     1566907.972      296653.154     1566524.806      296696.928
     1566266.473      296684.428     1566165.779      296763.594
     1566011.361      296832.643     1565985.387      296894.058
      1565746.89      297112.117     1565591.001       297130.22
     1565434.362      297205.799     1565227.301      297245.907
     1565049.403      297237.249     1564778.279       297356.65
     1564488.695      297542.414     1564274.036      297616.697
     1564206.336      297613.561     1564136.959      297544.497
     1563992.515      297523.664     1563910.356       297571.86
     1563869.414      297488.363     1563519.945      297385.122
     1563347.029      297222.969     1563279.668      297005.608
     1563289.737      296927.136     1563215.577      296811.604

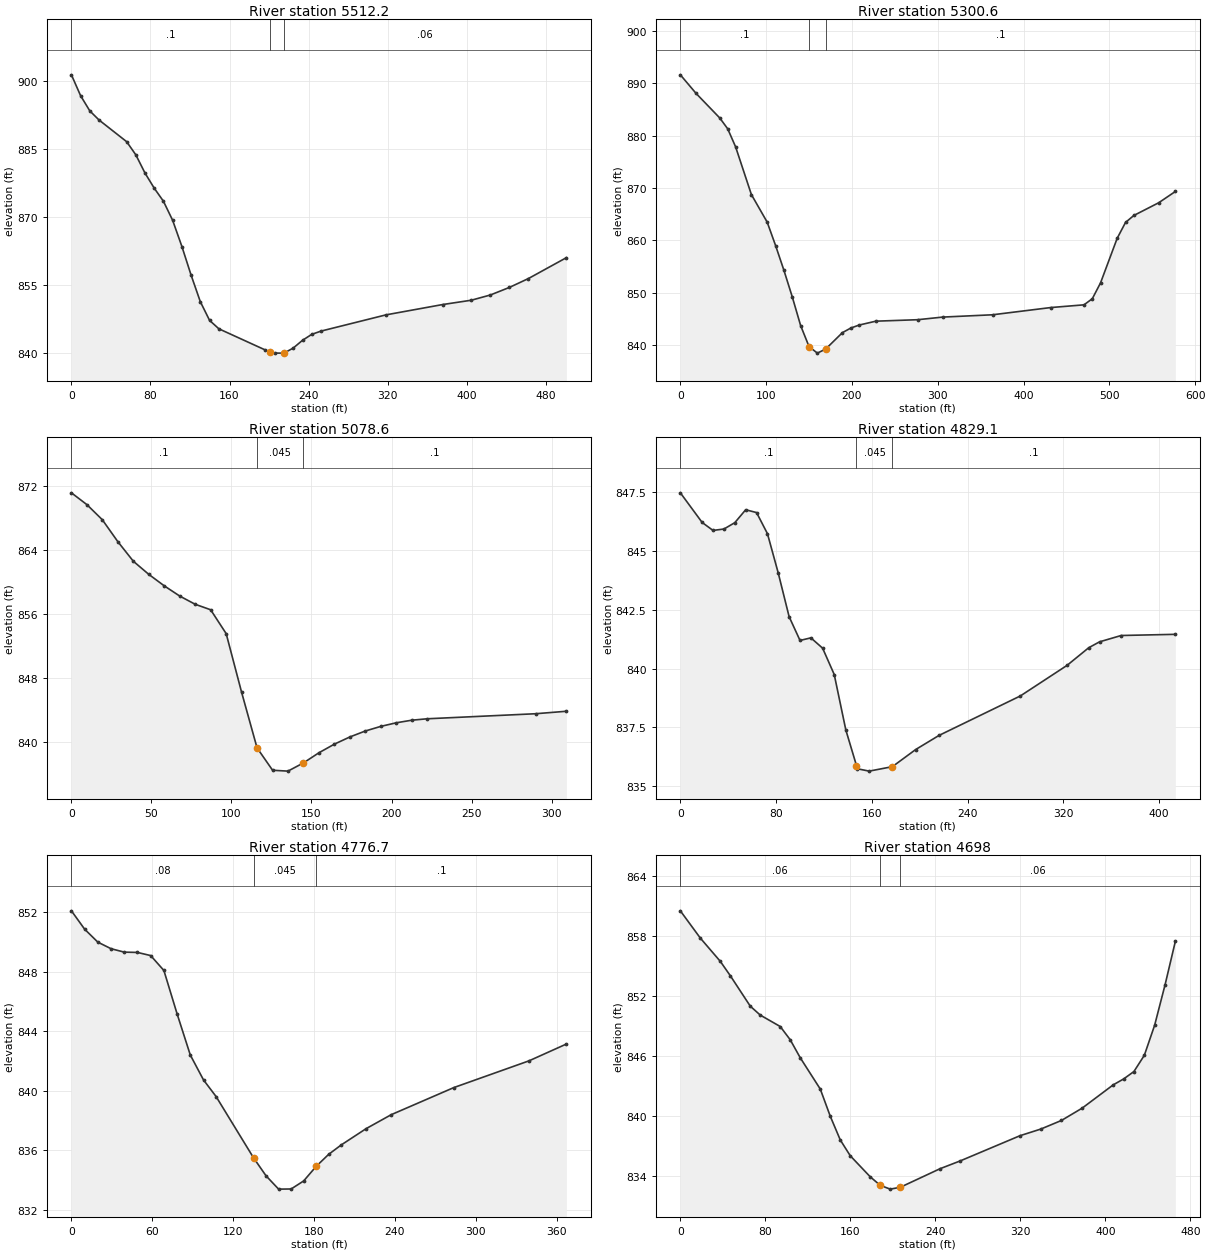
Type RM Length L Ch R = 1 ,5512.2  ,207.7,211.6,214.6
XS GIS Cut Line= 4
     1567841.979      296379.142     1567819.756      296507.614
     1567782.256      296701.364     1567826.527      296868.682
#Sta/Elev= 30
       0  901.47     9.3  896.85    18.6  893.49    27.9  891.48    55.9  886.67
    65.2  883.75    74.5  879.71    83.8  876.38    93.1  873.49   102.4  869.28
   111.8  863.46   121.1  857.13   130.4  851.27   139.8  847.12   149.2  845.26
   196.2  840.57  201.27840.2032   205.6  839.89     215  839.88   224.4     841
   233.8  842.72   243.2  844.04   252.6  844.76   318.3  848.35   375.8  850.64
   404.6  851.59   423.9  852.75   443.1  854.42   462.3  856.38   500.8  861.01
#Mann= 3 , 0 , 0
       0      .1       0  201.27    .045       0     215     .06       0
Bank Sta=201.27,215
XS Rating Curve= 0 ,0
Exp/Cntr=0.3,0.1

Type RM Length L Ch R = 1 ,5300.6  ,230.2,222,213.5
XS GIS Cut Line= 4
     1567677.352      296369.723     1567643.715       296465.21
     1567577.412      296648.445     1567482.169      296912.736
#Sta/Elev= 30
       0  891.61    18.4  888.05      46  883.36    55.2   881.3    64.4  877.86
    82.8  868.75   101.2  863.49     111  859.02   120.7   854.3   130.5  849.19
   140.2  843.74     150  839.73   159.7  838.48   169.4  839.26   188.9  842.39
   198.7  843.27   208.4  843.84   227.9  844.58   276.6  844.86   305.8  845.36
   363.9   845.8   431.7  847.18   470.5   847.7   480.2  848.87   489.8   851.9
   509.2  860.41   518.9  863.43   528.6  864.76   557.6  867.19     577  869.34
#Mann= 3 , 0 , 0
       0      .1       0     150    .045       0   169.4      .1       0
Bank Sta=150,169.4
XS Rating Curve= 0 ,0
Exp/Cntr=0.3,0.1

Type RM Length L Ch R = 1 ,5078.6  ,280.6,249.5,216.9
XS GIS Cut Line= 2
     1567404.999      296357.788      1567411.51      296667.033
#Sta/Elev= 26
       0  871.13     9.7  869.65    19.3  867.77      29  865.03    38.7  862.58
    48.3  860.95      58  859.51    67.7  858.23    77.3  857.21      87  856.52
    96.7  853.54   106.3  846.24     116  839.26   125.7  836.47   135.3  836.36
     145  837.39   154.7  838.66   164.3  839.73     174  840.63   183.6  841.37
   193.3  841.95     203   842.4   212.6  842.72   222.3   842.9     290  843.53
   309.3  843.84
#Mann= 3 , 0 , 0
       0      .1       0     116    .045       0     145      .1       0
Bank Sta=116,145
XS Rating Curve= 0 ,0
Exp/Cntr=0.3,0.1

Type RM Length L Ch R = 1 ,4829.1  ,45.5,52.4,59.7
XS GIS Cut Line= 4
     1567044.756      296412.041     1567113.622      296496.703
     1567306.727      296589.012     1567317.109      296678.968
#Sta/Elev= 27
       0  847.48    18.2  846.22    27.3  845.88    36.4  845.94    45.5  846.21
    54.6  846.76    63.7  846.64    72.8  845.74    81.8  844.07    90.9  842.21
     100   841.2   109.1  841.31   118.9  840.87   128.6  839.75   138.3  837.39
   147.2835.8761     148  835.74   157.8  835.64   177.2  835.83   196.7  836.56
   216.2  837.16   284.2  838.84   323.2  840.14   341.3  840.89   350.3  841.14
   368.4  841.41   413.7  841.46
#Mann= 3 , 0 , 0
       0      .1       0   147.2    .045       0   177.2      .1       0
Bank Sta=147.2,177.2
XS Rating Curve= 0 ,0
Exp/Cntr=0.3,0.1

Type RM Length L Ch R = 1 ,4776.7  ,68.8,78.7,89.4
XS GIS Cut Line= 4
     1567013.289      296442.423     1567074.185      296519.216
     1567205.347      296588.908     1567229.218       296707.18
#Sta/Elev= 25
       0  852.07     9.8  850.84    19.6  849.97    29.4  849.53    39.2   849.3
      49  849.28    58.8  849.07    68.6  848.07    78.4  845.16    88.2   842.4
      98  840.73   107.3  839.62   135.1  835.51   144.4   834.3   153.7  833.41
     163  833.42   172.3  833.96   181.6  834.94   190.8  835.74   200.1  836.37
   218.7  837.47   237.2   838.4   283.7  840.22   339.4  842.01   367.2  843.14
#Mann= 3 , 0 , 0
       0     .08       0   135.1    .045       0   181.6      .1       0
Bank Sta=135.1,181.6
XS Rating Curve= 0 ,0
Exp/Cntr=0.3,0.1

Type RM Length L Ch R = 1 ,4698    ,132.4,138.5,144.4
XS GIS Cut Line= 4
     1566938.419      296438.083     1567023.055       296550.93
     1567132.647      296691.989     1567174.965      296831.963
#Sta/Elev= 30
       0  860.49    18.8  857.77    37.6  855.45      47  854.02    65.8  850.98
    75.2  850.09      94  848.95   103.4  847.63   112.8  845.84   131.7  842.71
   141.1     840   150.5  837.64   159.9  836.06   178.7  833.96   188.1  833.11
   197.5  832.73   206.9  832.91   244.5  834.77   263.3  835.54   319.7  838.06
   339.2  838.72   358.7  839.58   378.2  840.81   407.4  843.13   417.2  843.72
   426.9  844.46   436.7  846.08   446.4  849.08   456.2  853.11   465.9  857.45
#Mann= 3 , 0 , 0
       0     .06       0   188.1    .045       0   206.9     .06       0
Bank Sta=188.1,206.9
XS Rating Curve= 0 ,0
Exp/Cntr=0.3,0.1

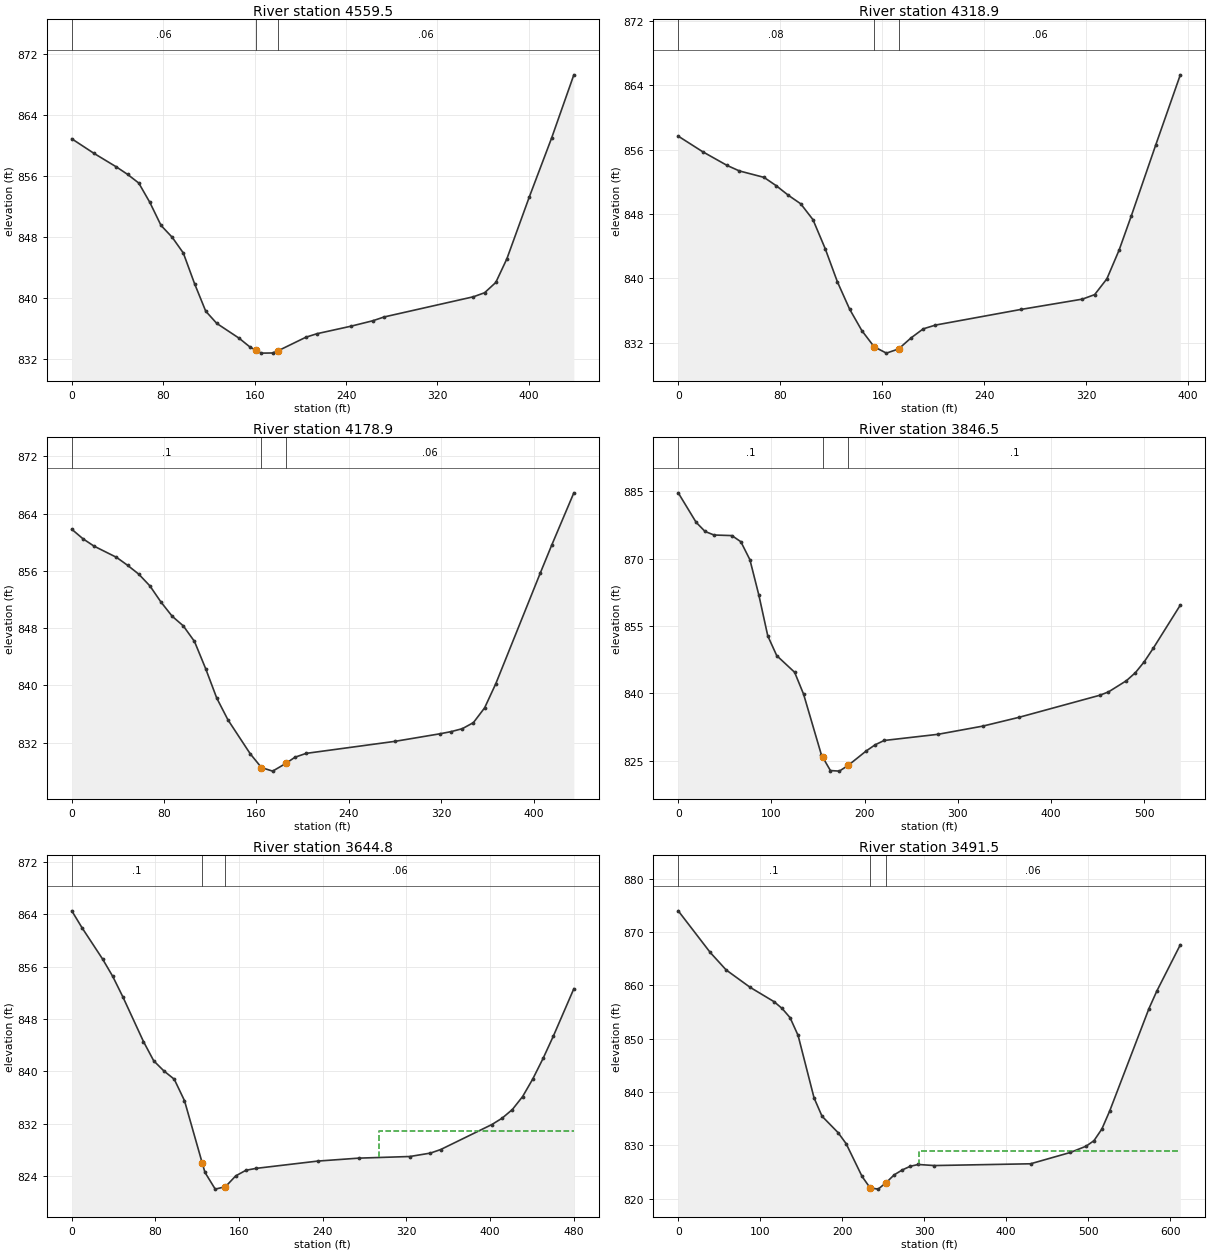
Type RM Length L Ch R = 1 ,4559.5  ,234.6,240.6,246.5
XS GIS Cut Line= 2
     1566863.246      296489.125     1567032.517      296894.506
#Sta/Elev= 30
       0  860.88    19.5  858.96      39  857.19    48.8  856.21    58.6  855.07
    68.3  852.53    78.1   849.5    87.9  847.94    97.6  845.88   107.4  841.87
   117.2  838.24   126.9  836.63   146.4  834.69   156.2   833.5  161.04833.1202
     166  832.73   175.7  832.75   180.8833.0608     205  834.83   214.8  835.29
   244.1  836.26   263.6  836.99   273.3  837.48   351.4  840.13   361.2  840.66
     371  842.01   380.7  845.12   400.2  853.19   419.8  860.96   439.3  869.28
#Mann= 3 , 0 , 0
       0     .06       0  161.04    .045       0   180.8     .06       0
Bank Sta=161.04,180.8
XS Rating Curve= 0 ,0
Exp/Cntr=0.3,0.1

Type RM Length L Ch R = 1 ,4318.9  ,139.9,140,140
XS GIS Cut Line= 2
     1566669.539      296513.604     1566721.753      296904.055
#Sta/Elev= 27
       0  857.69    19.2  855.75    38.4  854.04      48  853.36    67.3  852.56
    76.9  851.52    86.5  850.32    96.1  849.27   105.7   847.3   115.3  843.69
   124.9  839.55   134.5  836.15   144.1  833.48   153.7  831.48   163.3  830.69
   172.9  831.21   182.6  832.58   192.2  833.71   201.8  834.18     269  836.13
   317.1  837.41   326.7  837.97   336.3  839.94   345.9  843.52   355.5  847.79
   374.7  856.63   393.9  865.32
#Mann= 3 , 0 , 0
       0     .08       0   153.7    .045       0   172.9     .06       0
Bank Sta=153.7,172.9
XS Rating Curve= 0 ,0
Exp/Cntr=0.3,0.1

Type RM Length L Ch R = 1 ,4178.9  ,345.1,332.4,319
XS GIS Cut Line= 2
     1566530.433      296524.888     1566586.857      296956.138
#Sta/Elev= 30
       0  861.82     9.7  860.49    19.3  859.46    38.7   857.9    48.3  856.79
      58  855.55    67.7   853.9    77.3  851.64      87  849.66    96.6  848.32
   106.3  846.14     116  842.33   125.6  838.22   135.3  835.18   154.6  830.44
   164.3  828.52     174  828.02   185.7829.1216   193.3  829.96     203   830.5
   280.3  832.19     319  833.24   328.6  833.54   338.3  833.95   347.9   834.8
   357.6  836.86   367.3  840.24   405.9  855.73   415.6  859.55   434.9  866.91
#Mann= 3 , 0 , 0
       0      .1       0   164.3    .045       0   185.7     .06       0
Bank Sta=164.3,185.7
XS Rating Curve= 0 ,0
Exp/Cntr=0.3,0.1

Type RM Length L Ch R = 1 ,3846.5  ,196.7,201.7,206
XS GIS Cut Line= 3
     1566119.322      296578.534     1566305.954      296798.152
     1566410.729        297025.8
#Sta/Elev= 30
       0   884.7    19.2  878.13    28.8  876.09    38.4   875.3    57.6  875.17
    67.2   873.8    76.9   869.8    86.5  861.92    96.1  852.81   105.7  848.42
   124.9  844.71   134.5  839.84   153.7  826.26     155825.7932   163.3  822.81
   172.9  822.68   182.5  823.98   201.8  827.19   211.4  828.56     221  829.51
   278.6  830.88   326.8  832.71   365.3  834.65   452.1  839.57   461.7  840.33
     481  842.84   490.6  844.62   500.2  847.08   509.9  850.11   538.8  859.68
#Mann= 3 , 0 , 0
       0      .1       0     155    .045       0   182.5      .1       0
Bank Sta=155,182.5
XS Rating Curve= 0 ,0
Exp/Cntr=0.3,0.1

Type RM Length L Ch R = 1 ,3644.8  ,145.8,153.3,160.8
XS GIS Cut Line= 2
     1565994.409      296691.989     1566223.359      297114.081
#Sta/Elev= 30
       0   864.5     9.8  861.92    29.4  857.16    39.2  854.49      49  851.32
    68.6  844.54    78.4   841.6    88.2  840.05      98   838.8   107.8  835.53
  124.74826.0248   127.4  824.57   137.2  822.02     147  822.39   156.8  824.04
   166.6   824.9   176.4  825.19   235.2   826.3   274.4  826.75   323.4     827
     343  827.52   352.8  828.06   401.8  831.88   411.6  832.85   421.4  834.17
   431.2  836.15     441  838.86   450.8  841.98   460.6  845.38   480.2  852.61
#Mann= 3 , 0 , 0
       0      .1       0  124.74    .045       0     147     .06       0
#XS Ineff= 2 , 0
                          293.62          830.89
Permanent Ineff=
       F       F
Bank Sta=124.74,147
XS Rating Curve= 0 ,0
Exp/Cntr=0.3,0.1

Type RM Length L Ch R = 1 ,3491.5  ,51.1,52.6,56.1
XS GIS Cut Line= 4
     1565794.409      296773.196     1565949.562      296855.009
     1566005.958      297143.038     1566082.604      297264.515
#Sta/Elev= 30
       0  873.96      39  866.16    58.5  862.87    87.7  859.62   116.9  856.93
   126.7  855.66   136.4  853.94   146.2  850.61   165.7  838.89   175.4  835.46
     195  832.38   204.8  830.32   224.3  824.16   234.1  822.02   243.9  821.79
   253.7  823.02   263.4  824.46   273.2  825.38     283  826.07   292.8  826.41
   312.4  826.21   429.8  826.54   478.5  828.67   497.6  829.84   507.2  830.88
   516.8  833.06   526.4  836.46   574.2  855.62   583.8  858.91   612.5   867.6
#Mann= 3 , 0 , 0
       0      .1       0   234.1    .045       0   253.7     .06       0
#XS Ineff= 2 , 0
                          293.17          828.97
Permanent Ineff=
       F       F
Bank Sta=234.1,253.7
XS Rating Curve= 0 ,0
Exp/Cntr=0.3,0.1

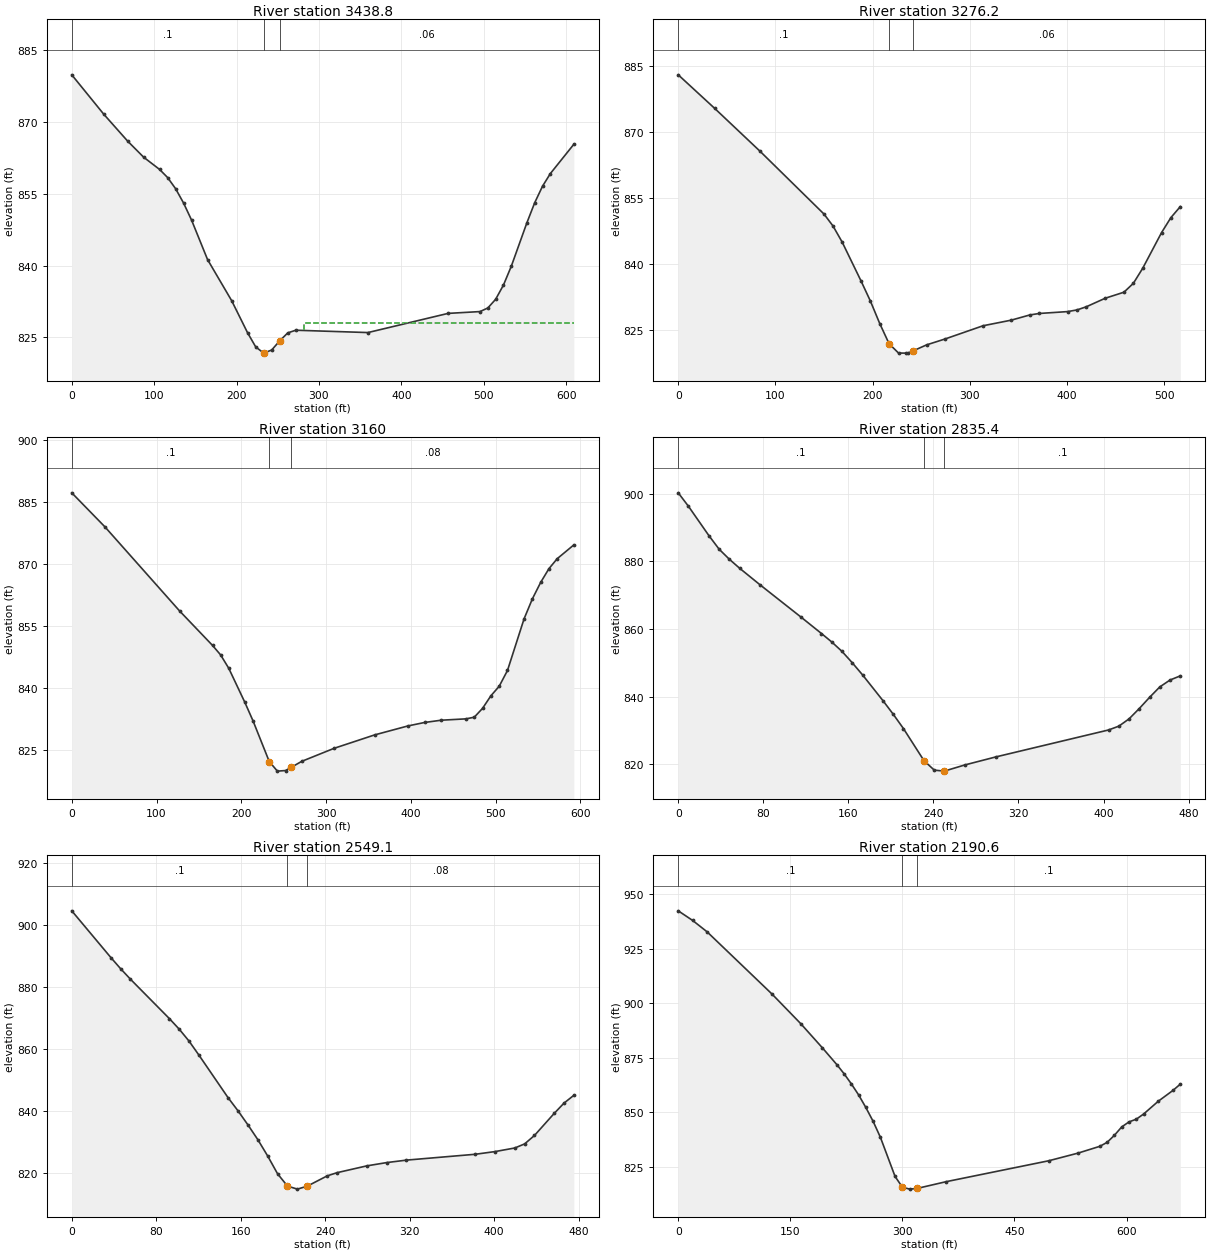
Type RM Length L Ch R = 1 ,3438.8  ,173.1,162.7,149.9
XS GIS Cut Line= 4
     1565758.819      296816.425     1565909.796      296882.409
     1565967.435      297198.318     1566024.444      297307.744
#Sta/Elev= 30
       0  879.91    38.8  871.68    67.8  866.05    87.2  862.69   106.6  860.12
   116.3  858.43     126   856.1   135.7  853.09   145.4  849.52   164.8  841.27
     194  832.69   213.4  825.95   223.2  823.02   232.9  821.71   242.6  822.36
   252.4  824.29   262.1  825.94   271.8   826.5   359.4  826.01   456.7  830.02
   495.4   830.4   504.9  831.15   514.4  832.97   523.9  835.95   533.4  839.88
   552.3  848.96   561.8  853.16   571.3  856.62   580.8  859.26   609.3  865.39
#Mann= 3 , 0 , 0
       0      .1       0   232.9    .045       0   252.4     .06       0
#XS Ineff= 2 , 0
                          281.92          828.04
Permanent Ineff=
       F       F
Bank Sta=232.9,252.4
XS Rating Curve= 0 ,0
Exp/Cntr=0.3,0.1

Type RM Length L Ch R = 1 ,3276.2  ,105.9,116.2,126.3
XS GIS Cut Line= 3
      1565701.44      296868.855     1565779.044      297018.638
     1565964.808      297312.909
#Sta/Elev= 30
       0  882.91    37.5   875.3    84.4  865.53     150  851.33   159.3  848.61
   168.7  844.97     188  836.21   197.7  831.62   207.4  826.48     217  821.91
   226.7   819.8   234.6  819.78   236.4  819.78   242.1820.3322   255.7  821.66
     275  823.02   313.7  825.99   342.7  827.26     362  828.45   371.7  828.78
   400.7   829.2   410.4  829.58     420   830.3   439.4  832.23   458.7   833.6
   468.4  835.62     478  839.03   497.4  847.12     507  850.52   516.7  853.02
#Mann= 3 , 0 , 0
       0      .1       0     217    .045       0   242.1     .06       0
Bank Sta=217,242.1
XS Rating Curve= 0 ,0
Exp/Cntr=0.3,0.1

Type RM Length L Ch R = 1 ,3160    ,325.2,324.5,323.4
XS GIS Cut Line= 4
     1565647.708      296886.043     1565699.791      297033.612
      1565722.36      297233.265     1565774.444      297462.432
#Sta/Elev= 30
       0  887.29    39.1  879.04   127.2  858.64   166.1  850.27   175.6  847.98
   185.2  844.74   204.3  836.43   213.9  831.96     233  822.11   242.6  819.78
   252.2  819.92   259.2820.7231   271.3  822.15   309.6  825.32   357.4  828.57
   396.6  830.74   416.2  831.58   435.8  832.13   465.1  832.46   474.9  832.86
   484.7  835.01   494.5  838.05   504.3  840.36   514.1   844.2   533.7  856.74
   543.5  861.58   553.3  865.58     563  868.89   572.8  871.32   592.4  874.66
#Mann= 3 , 0 , 0
       0      .1       0     233    .045       0   259.2     .08       0
Bank Sta=233,259.2
XS Rating Curve= 0 ,0
Exp/Cntr=0.3,0.1

Type RM Length L Ch R = 1 ,2835.4  ,280.4,286.3,291.5
XS GIS Cut Line= 3
     1565316.241      296988.213     1565391.024      297122.805
     1565438.854      297437.432
#Sta/Elev= 30
       0  900.21     9.6  896.24    28.9  887.54    38.5  883.54    48.1  880.58
    57.7  877.94      77  873.02   115.5  863.49   134.7  858.65   144.4  856.14
     154  853.37   163.6  850.03   173.3  846.44   192.6  838.79   202.2   834.8
   211.8  830.57   231.1   821.1   240.8  818.28   250.2  817.99   250.4818.0081
   269.7  819.83   298.6  822.18   404.7  830.15   414.4  831.28     424  833.43
   433.6  836.48   443.3  839.79   452.9  842.87   462.6  844.92   472.2  846.13
#Mann= 3 , 0 , 0
       0      .1       0   231.1    .045       0   250.4      .1       0
Bank Sta=231.1,250.4
XS Rating Curve= 0 ,0
Exp/Cntr=0.3,0.1

Type RM Length L Ch R = 1 ,2549.1  ,371,358.5,344.1
XS GIS Cut Line= 4
     1565087.291      297052.232     1565128.524      297194.376
     1565112.248      297362.562     1565161.076      297513.387
#Sta/Elev= 30
       0  904.62      37  889.54    46.2  885.95    55.5  882.56    92.5  869.79
   101.8  866.38     111  862.57   120.2  858.13     148  844.28   157.4  840.04
   166.8   835.5   176.2  830.72   185.6   825.4   194.9  819.69   204.3815.7095
   213.7  814.73   223.1   815.7   241.9  819.01   251.3  820.05   279.4  822.24
   298.2   823.3     317   824.1   382.2  825.99   400.9  826.86   419.6  828.02
   428.9  829.34   438.2  832.06   456.9  839.19   466.2  842.52   475.5  845.03
#Mann= 3 , 0 , 0
       0      .1       0   204.3    .045       0   223.1     .08       0
Bank Sta=204.3,223.1
XS Rating Curve= 0 ,0
Exp/Cntr=0.3,0.1

Type RM Length L Ch R = 1 ,2190.6  ,265.5,267.1,268.5
XS GIS Cut Line= 3
     1564662.465      297070.071     1564759.687       297280.14
     1564969.756      297667.293
#Sta/Elev= 30
       0  942.41    19.3  937.99    38.6  932.78   125.4  904.25     164  890.61
   192.9  879.54   212.2  871.85   221.8  867.71   231.5  863.08   241.3  857.99
     251   852.2   260.8  845.82   270.6  838.45   290.2   820.5     300  815.56
   309.8  814.67   319.6  814.98   358.7   818.1   495.8  827.68   534.9  831.18
   564.3  834.32   574.1  836.16   583.8  839.38   593.6  843.23   603.4  845.54
   613.2  846.79     623  849.18   642.6  855.04   662.2  859.99     672  862.86
#Mann= 3 , 0 , 0
       0      .1       0     300    .045       0   319.6      .1       0
Bank Sta=300,319.6
XS Rating Curve= 0 ,0
Exp/Cntr=0.3,0.1

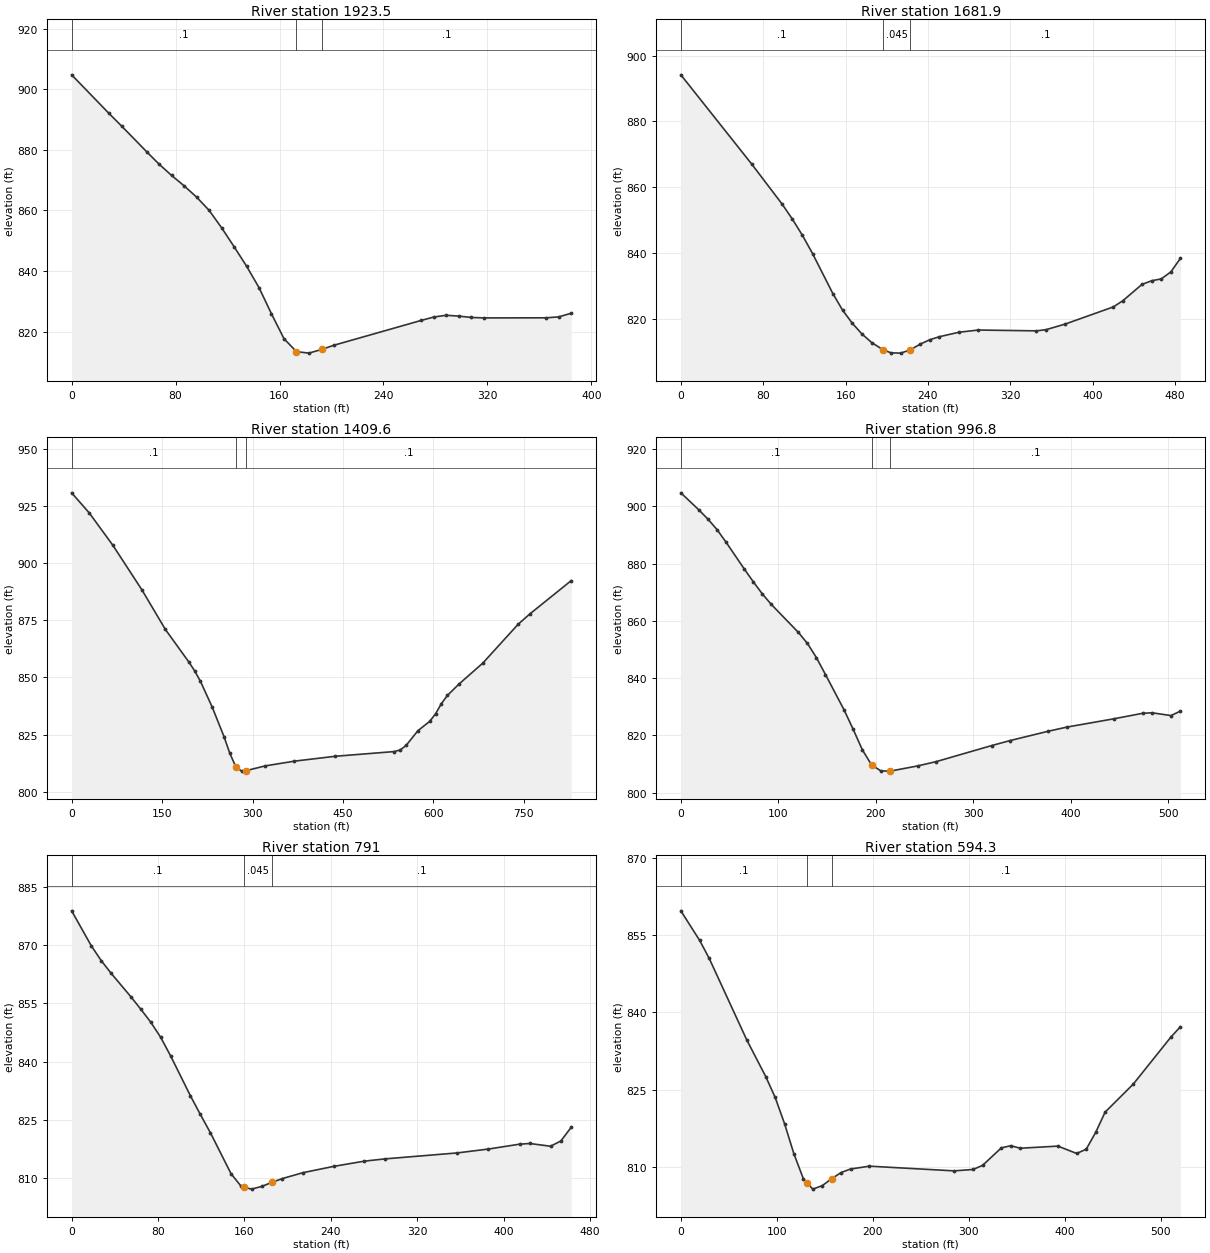
Type RM Length L Ch R = 1 ,1923.5  ,242.1,241.6,240.2
XS GIS Cut Line= 2
     1564492.673      297319.159     1564653.263      297668.552
#Sta/Elev= 28
       0  904.77    28.8     892    38.4  887.88    57.7  879.39    67.3  875.27
    76.9  871.56    86.5  868.14    96.1  864.42   105.8  860.02   115.4  854.28
     125  848.03   134.6   841.6   144.2  834.51   153.8  825.84   163.4  817.66
     173  813.36   182.6  812.87   192.3  814.07   201.9  815.48   269.2  823.69
   278.8   824.8   288.4  825.37     298  825.09   307.6  824.65   317.2   824.5
   365.3  824.53   374.9  824.84   384.5  826.05
#Mann= 3 , 0 , 0
       0      .1       0     173    .045       0   192.3      .1       0
Bank Sta=173,192.3
XS Rating Curve= 0 ,0
Exp/Cntr=0.3,0.1

Type RM Length L Ch R = 1 ,1681.9  ,257.8,272.2,285.4
XS GIS Cut Line= 4
     1564325.572      297384.263     1564327.742      297531.833
     1564416.718      297697.848     1564462.291      297839.993
#Sta/Elev= 30
       0  894.15    68.9  866.99    98.4  854.84   108.2  850.34   118.1  845.35
   127.9  839.83   147.6  827.68     157  822.66   166.4  818.68   175.8  815.41
   185.3  812.78   196.1810.6201   204.1  809.65   213.5  809.56   222.9  810.56
   232.4  812.28   241.8  813.64   251.2  814.56     270   815.9   288.8  816.58
   345.3  816.33   354.6  816.68   373.3   818.4   419.9  823.59   429.2  825.47
   447.9  830.46   457.2  831.55   466.6  832.13   475.9  834.25   485.2  838.39
#Mann= 3 , 0 , 0
       0      .1       0   196.1    .045       0   222.9      .1       0
Bank Sta=196.1,222.9
XS Rating Curve= 0 ,0
Exp/Cntr=0.3,0.1

Type RM Length L Ch R = 1 ,1409.6  ,408.1,412.9,412.2
XS GIS Cut Line= 4
     1564185.034      297274.932     1564135.815      297452.666
     1564095.597      297771.363      1564021.84      298085.696
#Sta/Elev= 30
       0  930.68    29.1  921.93      68  907.89   116.5  888.29   155.3  871.04
   194.2  856.81   203.9  852.92   213.6  848.31   233.1  837.05   252.6  824.19
   262.3  816.86     272  811.08   281.8  809.06   289.8809.2982   320.7  811.33
   369.4  813.42   437.5  815.56     535  817.61   544.8  818.31   554.6  820.26
   574.1  826.69   593.7  830.79   603.5  834.09   613.3  838.61   623.1  842.13
   642.6  847.17   681.8  856.25   740.5  873.25     760  877.78   828.5  892.32
#Mann= 3 , 0 , 0
       0      .1       0     272    .045       0   289.8      .1       0
Bank Sta=272,289.8
XS Rating Curve= 0 ,0
Exp/Cntr=0.3,0.1

Type RM Length L Ch R = 1 ,996.8   ,207.2,205.8,203.3
XS GIS Cut Line= 4
     1563889.374      297300.713     1563814.505      297428.751
     1563767.847      297602.362     1563695.147      297771.633
#Sta/Elev= 30
       0  904.73    18.5  898.76    27.8  895.53    37.1  891.88    46.4  887.46
    64.9  878.18    74.2  873.68    83.4  869.48    92.7  865.75   120.5  855.96
   129.8   852.1     139  847.15   148.3  841.23   167.2  828.99   176.7   822.1
   186.2  814.86   195.6  809.64   205.1  807.56   214.6  807.47   242.9  809.29
   261.9   810.8   318.6  816.39   337.8  818.17   376.6   821.4     396  822.87
   444.4  825.78   473.5  827.68   483.2  827.86   502.6  826.89   512.3  828.45
#Mann= 3 , 0 , 0
       0      .1       0   195.6    .045       0   214.6      .1       0
Bank Sta=195.6,214.6
XS Rating Curve= 0 ,0
Exp/Cntr=0.3,0.1

Type RM Length L Ch R = 1 ,791     ,190.2,196.7,202.7
XS GIS Cut Line= 4
     1563666.067      297254.706     1563619.409      297364.298
     1563587.725      297542.076     1563504.175       297682.05
#Sta/Elev= 30
       0   878.9    18.3  869.83    27.5  866.02    36.6  862.78      55  856.69
    64.1  853.51    73.3  850.17    82.5  846.26    91.6  841.52     110   831.2
   119.1  826.43   128.6  821.62   147.6  811.11   157.1  807.81  159.87807.6079
   166.6  807.12   176.1  807.82   185.6  808.88   195.1  809.84   214.2  811.36
   242.7  812.99   271.2  814.34   290.2  814.92   357.2  816.46     386  817.46
   414.8  818.71   424.4  818.89   443.5  818.18   453.1  819.54   462.7  823.08
#Mann= 3 , 0 , 0
       0      .1       0  159.87    .045       0   185.6      .1       0
Bank Sta=159.87,185.6
XS Rating Curve= 0 ,0
Exp/Cntr=0.3,0.1

Type RM Length L Ch R = 1 ,594.3   ,72.1,71.6,70.9
XS GIS Cut Line= 2
     1563516.631      297181.182     1563290.329      297649.715
#Sta/Elev= 30
       0  859.68    19.6  853.94    29.4  850.51    68.7  834.63    88.4  827.55
    98.2  823.51     108  818.42   117.8  812.53   127.6  807.73   131.8806.8686
   137.4  805.72   147.3   806.4   157.1  807.74   166.9  808.94   176.7  809.62
   196.4  810.17   284.7  809.26   304.3  809.53   314.2  810.32   333.8  813.72
   343.6  814.14   353.4  813.65   392.7  814.06   412.3  812.63   422.2  813.47
     432   816.7   441.8  820.64   471.2  826.09   510.5  835.23   520.3  837.21
#Mann= 3 , 0 , 0
       0      .1       0   131.8    .045       0   157.1      .1       0
Bank Sta=131.8,157.1
XS Rating Curve= 0 ,0
Exp/Cntr=0.3,0.1

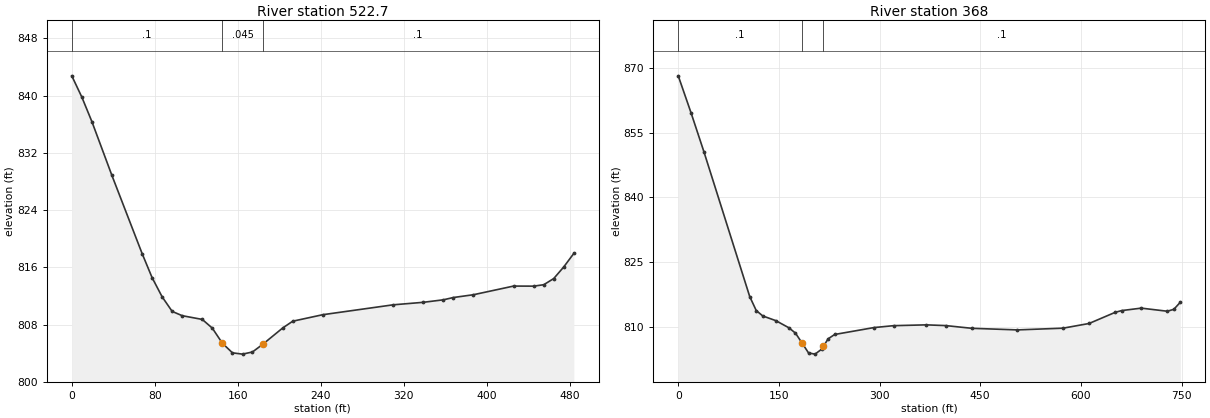
Type RM Length L Ch R = 1 ,522.7   ,135.6,154.7,172.7
XS GIS Cut Line= 2
     1563456.128      297136.173     1563254.739      297576.277
#Sta/Elev= 30
       0  842.75     9.7  839.78    19.4  836.35    38.7  828.83    67.8  817.92
    77.4  814.56    87.1  811.87    96.8  809.83   106.5  809.23   125.8  808.71
   135.5  807.49   145.2  805.38   154.9  804.04   164.6  803.86   174.2  804.16
   183.9  805.21   203.3  807.51     213  808.46     242  809.37   309.8  810.75
   338.8   811.1   358.2  811.45   367.8  811.77   387.2  812.16   425.9  813.37
   445.3  813.36     455  813.56   464.6  814.42   474.3  816.05     484  817.94
#Mann= 3 , 0 , 0
       0      .1       0   145.2    .045       0   183.9      .1       0
Bank Sta=145.2,183.9
XS Rating Curve= 0 ,0
Exp/Cntr=0.3,0.1

Type RM Length L Ch R = 1 ,368     ,371.8,368,361.8
XS GIS Cut Line= 4
     1563500.399      297083.743     1563473.489      297093.291
     1563150.572      297202.666     1563249.531      297568.118
#Sta/Elev= 30
       0  868.16      19  859.62    38.3  850.53   106.5  816.96   116.2  813.72
     126  812.45   145.4  811.37   164.9  809.71   174.7  808.47   184.4   806.2
   194.2  803.87   203.9   803.6   213.6  804.74  216.15805.3697   223.4  807.16
   233.1  808.16   291.6  809.76   320.8   810.2   369.5  810.39   398.6  810.22
   437.4  809.59   505.4  809.22   573.4  809.62   612.2  810.71     651  813.29
   660.7   813.7   689.9  814.27   728.7  813.55   738.4  813.99   748.1  815.63
#Mann= 3 , 0 , 0
       0      .1       0   184.4    .045       0  216.15      .1       0
Bank Sta=184.4,216.15
XS Rating Curve= 0 ,0
Exp/Cntr=0.3,0.1

Chan Stop Cuts=-1
Use User Specified Reach Order=0
Composite Channel Slope=5